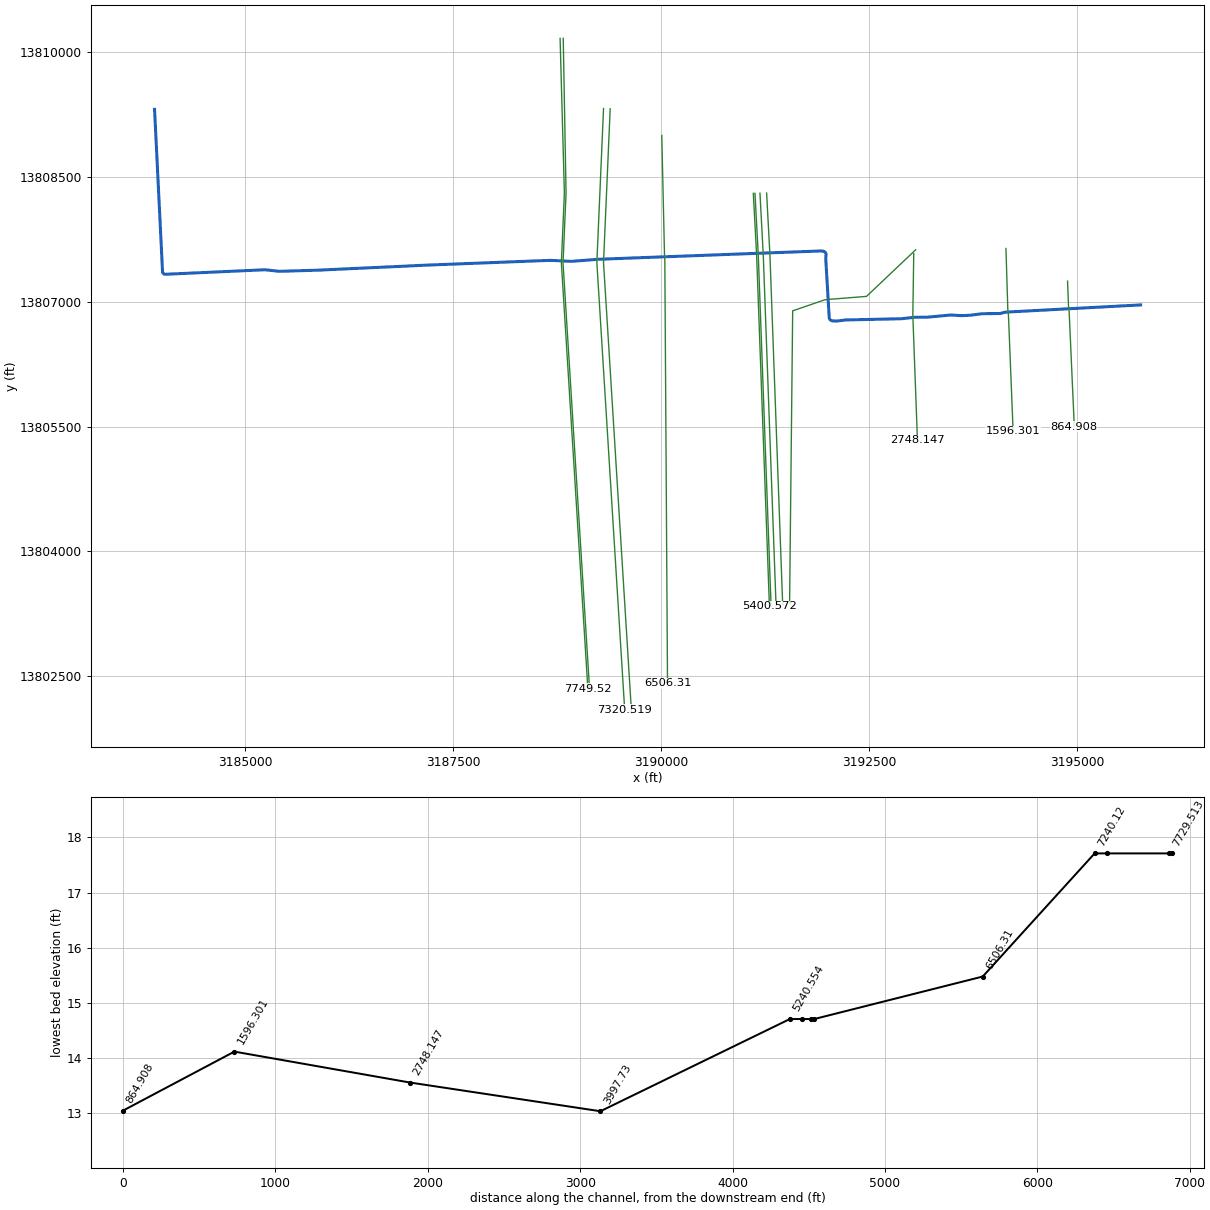
--- B115-00-00.prj (project) ---

Proj Title=B115-00-00
Current Plan=p02
Default Exp/Contr=.3,.1
English Units
Geom File=g01
Flow File=f01
Flow File=f02
Plan File=p01
Plan File=p02
Y Axis Title=Elevation
X Axis Title(PF)=Main Channel Distance
X Axis Title(XS)=Station
BEGIN DESCRIPTION:
HCFCD MODEL SUMMARY METADATA
The purpose of this summary is to document the high points of hydrologic and hydraulic models filed within the HCFCD Model and Map Management (M3) system.  The document includes references to the project that prompted the creation or update of the model.
DESCRIPTION OF PROJECT:
The following model was the hydraulic model which represented the effective condition of Harris County's watersheds.
PURPOSE OF PROJECT:
Development of effective models to support the National Flood Insurance Program.
HCFCD Watershed Unit ID: B
M3 Study Identifier: 2007_Effective_B
Engineer: HCFCD
Project Name: EffectiveFEMA Study for watershed Armand Bayou (B)
Study Completion Date: 6/18/2007
FEMA Case Number: [No Data]
FEMA Approval Date: [No Date in Database]
Vertical Datum: NAVD 1988
Datum Note: 2001 ADJ
HYDRAULICS
HCFCD Unit No.:  B115-00-00
Hydraulic Program Name: HEC-RAS
Hydraulic Program Version: 3.0.1
Steady Hydraulic Model: Yes
Unsteady Hydraulic Model: No
Update 1:
The effective FEMA hydraulic model for unit number B100-00-00 has been updated by FEMA LOMR 14-06-4559P with an effective date of 10/16/2015.
END DESCRIPTION:
DSS File=dss
DSS Export Rating Curves= 0
DSS Export Rating Curve Sorted= 0
DSS Export Volume Flow Curves= 0
DXF OffsetX= 0
DXF OffsetY= 0
DXF ScaleX= 1
DXF ScaleY= 10

--- B115-00-00.p02 (plan) ---

Plan Title=Effective Floodway 2015
Version=Version 3.0.1  May 2012
Short Identifier=EFF+FW LOMR
Geom File=g01
Flow File=f02
Subcritical Flow
K Sum by GR= 0
Std Step Tol= 0.01
Critical Tol= 0.01
Num of Std Step Trials= 20
Max Error Tol= 0.3
Flow Tol Ratio= 0.001
Split Flow NTrial= 30
Split Flow Tol= 0.02
Split Flow Ratio= 0.02
Log Output Level= 0
Friction Slope Method= 0
Unsteady Friction Slope Method= 2
Secant Critical Depth
Global Vel Dist= 0 , 0 , 0
Global Log Level= 0
CheckData=True
Encroach Param=-1 ,0,0, 2
Encroach River=B115-00-00
Encroach Reach=Main
Encroach Node=7749.52
       1    4960    5040
Encroach Node=7729.513
       1    4952    5032
Encroach Node=7521.9
       1    4960    5040
Encroach Node=7320.519
       1    4960    5040
Encroach Node=7240.12
       1    4960    5040
Encroach Node=6506.31
       1    4971    5051
Encroach Node=5400.572
       1    4960    5040
Encroach Node=5380.569
       1    4960    5040
Encroach Node=5350.57
       1    4960    5040
Encroach Node=5320.562
       1    4960    5040
Encroach Node=5240.554
       1    4940    5020
Encroach Node=3997.73
       1    4953    5040
Encroach Node=2748.147
       1 4958.17    5037
Encroach Node=1596.301
       1 4955.11 5036.19
Encroach Node=864.908
       1 4989.28 5055.16
Encroach Reach=B115-00-00_0009
Encroach Node=7749.52
       1    4960    5040
Encroach Node=7729.513
       1    4952    5032
Encroach Node=7521.9
       1    4960    5040
Encroach Node=7320.519
       1    4960    5040
Encroach Node=7240.12
       1    4960    5040
Encroach Node=6506.31
       1    4971    5051
Encroach Node=5400.572
       1    4960    5040
Encroach Node=5380.569
       1    4960    5040
Encroach Node=5350.57
       1    4960    5040
Encroach Node=5320.562
       1    4960    5040
Encroach Node=5240.554
       1    4940    5020
Encroach Node=3997.73
       1    4953    5040
Encroach Node=2748.147
       1 4958.17    5037
Encroach Node=1596.301
       1 4955.11 5036.19
Encroach Node=864.908
       1 4989.28 5055.16
BEGIN DESCRIPTION:
FEMA Effective Floodway June 2007 + LOMR 14-06-4559P
END DESCRIPTION:
Computation Interval=1HOUR
Output Interval=1HOUR
Run HTab= 0
Run UNet= 0
Run PostProcess= 0
UNET Theta= 1
UNET ZTol= 0.02
UNET ZSATol= 0.1
UNET MxIter= 20
UNET MaxInSteps= 20
UNET DtIC= 0
UNET DtMin= 0
UNET MaxCRTS= 20
UNET WFStab= 2
UNET SFStab= 1
UNET WFX= 1
UNET SFX= 1
UNET Convert EG Bridges=-1
UNET Use Existing IB Tables=-1
Instantaneous Interval=1HOUR
DSS File=dss
Write IC File= 0
IC Time=0
Write Velocity= 0
Write Detailed= 0

--- B115-00-00.p01 (plan) ---

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Plan Title=Effective Multi-Profile 2015
Short Identifier=Eff+LOMR MP
Geom File=g01
Flow File=f01
Friction Slope Method= 1
Parabolic Critical Depth
Encroach Param=-1 ,0,0, 0
FEMA Effective Multi-Profile June 2007 + LOMR 14-06-4559P

--- B115-00-00.f02 (steady flow) ---

Flow Title=Effective Floodway 2015
Version=Version 3.0.1  May 2012
Number of Profiles= 2
Profile Names=1PCT_100yr, 1PCTFloodway_100yrFW
River Rch & RM=B115-00-00,B115-00-00_0009 ,7749.52
    1231    1231
River Rch & RM=B115-00-00,B115-00-00_0009 ,6506.31
    1351    1351
River Rch & RM=B115-00-00,B115-00-00_0009 ,5400.572
    1883    1883
River Rch & RM=B115-00-00,B115-00-00_0009 ,3997.73
    2024    2024
River Rch & RM=B115-00-00,B115-00-00_0009 ,2748.147
    2176    2176
River Rch & RM=B115-00-00,B115-00-00_0009 ,1596.301
    2327    2327
River Rch & RM=B115-00-00,B115-00-00_0009 ,864.908
    2428    2428
Boundary for River Rch & Prof#=B115-00-00,B115-00-00_0009 , 1
Up Type= 0
Dn Type= 3
Dn Slope=.002
Boundary for River Rch & Prof#=B115-00-00,B115-00-00_0009 , 2
Up Type= 0
Dn Type= 3
Dn Slope=.002
DSS Import GetInterval= 0
DSS Import GetPeak= 0
DSS Import FillOption= 0

--- B115-00-00.f01 (steady flow) ---

Flow Title=Effective Multi-Profile 2015
Version=Version 3.0.1  May 2012
Number of Profiles= 4
Profile Names=10PCT_10yr, 2PCT_50yr, 1PCT_100yr, 0.2PCT_500yr
River Rch & RM=B115-00-00,B115-00-00_0009 ,7749.52
     755    1066    1231    1681
River Rch & RM=B115-00-00,B115-00-00_0009 ,6506.31
     828    1170    1351    1845
River Rch & RM=B115-00-00,B115-00-00_0009 ,5400.572
    1096    1619    1883    2524
River Rch & RM=B115-00-00,B115-00-00_0009 ,3997.73
    1179    1741    2024    2713
River Rch & RM=B115-00-00,B115-00-00_0009 ,2748.147
    1267    1872    2176    2917
River Rch & RM=B115-00-00,B115-00-00_0009 ,1596.301
    1355    2002    2327    3120
River Rch & RM=B115-00-00,B115-00-00_0009 ,864.908
    1414    2089    2428    3255
Boundary for River Rch & Prof#=B115-00-00,B115-00-00_0009 , 1
Up Type= 0
Dn Type= 3
Dn Slope=.002
Boundary for River Rch & Prof#=B115-00-00,B115-00-00_0009 , 2
Up Type= 0
Dn Type= 3
Dn Slope=.002
Boundary for River Rch & Prof#=B115-00-00,B115-00-00_0009 , 3
Up Type= 0
Dn Type= 3
Dn Slope=.002
Boundary for River Rch & Prof#=B115-00-00,B115-00-00_0009 , 4
Up Type= 0
Dn Type= 3
Dn Slope=.002
DSS Import GetInterval= 0
DSS Import GetPeak= 0
DSS Import FillOption= 0

--- B115-00-00.g01 (geometry) ---

Geom Title=B115-00-00 June 2007
Version=Version 3.0.1  Mar 2001

River Reach=B115-00-00      ,B115-00-00_0009
Reach XY= 30
        3183908.       13809315.       3184004.5       13807354.
        3184026.       13807331.       3185238.5       13807386.
        3185408.       13807367.      3185876.25       13807381.
       3187191.5       13807442.      3188664.75       13807499.
      3188919.75       13807487.        3189246.       13807512.
      3191920.25       13807612.       3191953.5       13807609.
        3191974.       13807596.       3191983.5       13807576.
       3191979.5       13807519.      3192021.75       13806801.
       3192034.5       13806781.      3192056.75       13806771.
       3192112.5       13806769.      3192217.75       13806782.
      3192890.25       13806797.      3193041.25       13806814.
      3193208.25       13806816.      3193483.75       13806842.
        3193612.       13806834.      3193715.75       13806839.
       3193858.5       13806857.      3194076.75       13806860.
       3194137.5       13806876.        3195766.       13806963.

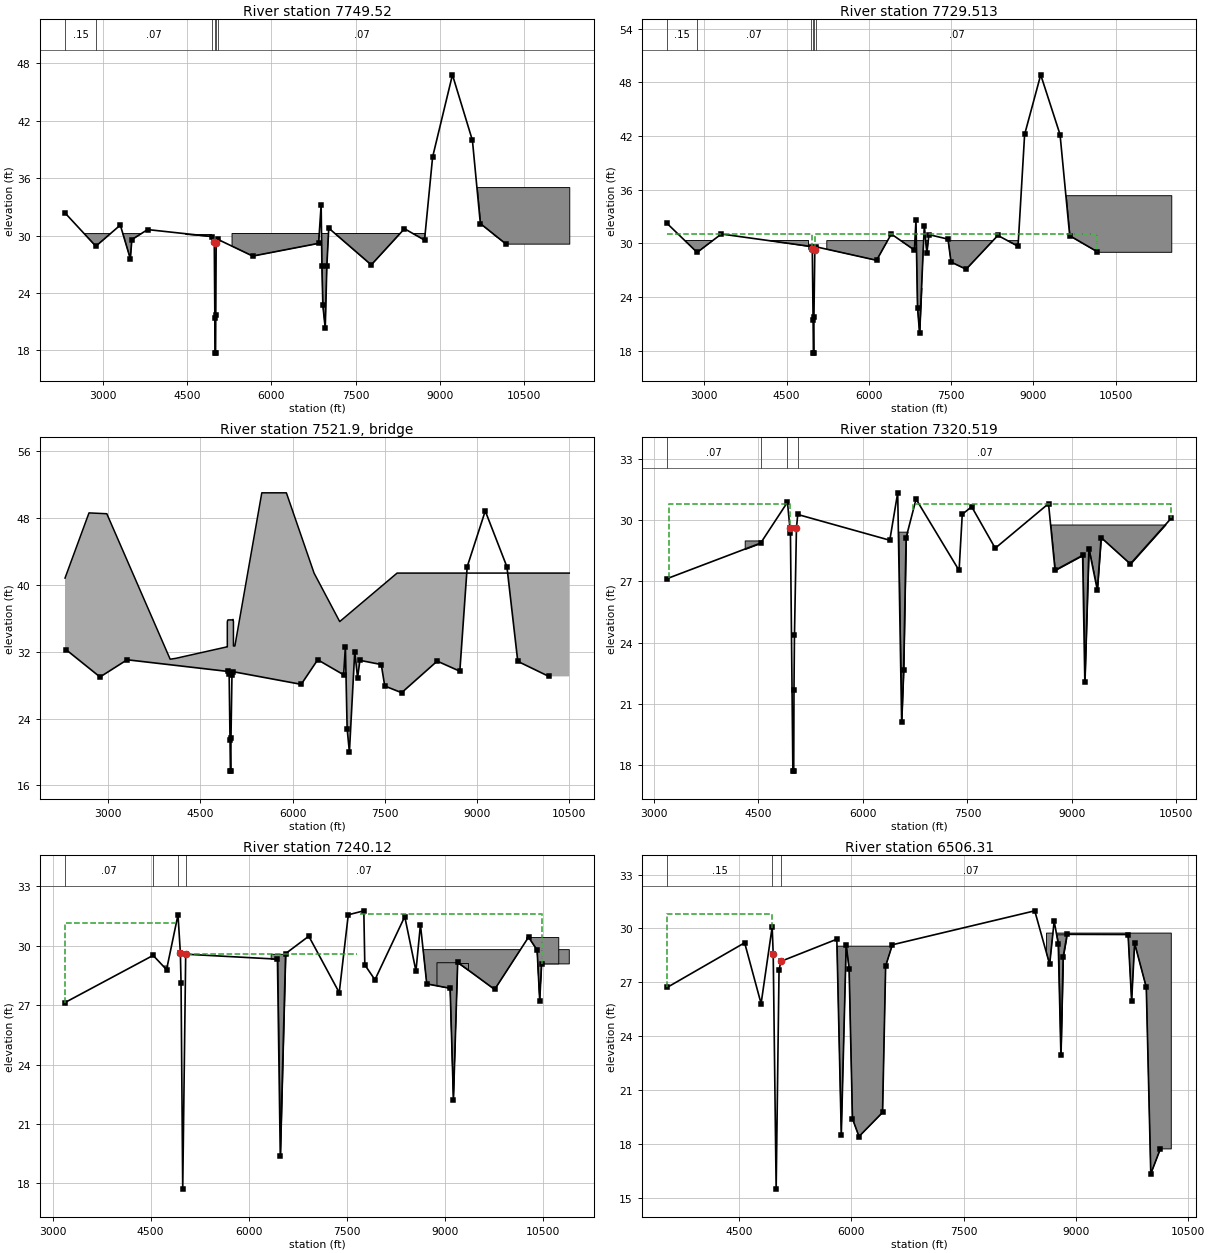
Type RM Length L Ch R = 1 ,7749.52 ,20.02,20.01,20.24
XS GIS Cut Line= 6
     3188784.964    13810168.864      3188836.65     13808309.84
     3188801.986    13807509.568     3188799.715    13807475.033
     3188852.019    13806634.698     3189119.075    13802344.039
#Sta/Elev= 30
 2327.82   32.36 2876.36   28.88 3311.83   31.09 3490.43   27.56 3516.71   29.57
 3796.96   30.62 4938.97   29.89 4983.22   29.36  4993.4    21.4 4999.75   17.71
 5006.16   17.72    5010    21.7 5016.78   29.25 5045.34    29.6 5666.97   27.85
 6839.24   29.18 6884.32   33.21 6898.03   26.86 6914.66   22.71 6957.11    20.3
 6985.41   26.77 7019.58   30.77 7775.88   26.93 8366.22   30.71 8723.39   29.52
 8867.14    38.2 9220.05   46.79 9575.35   39.94 9716.42   31.2510164.12   29.15
#Mann= 6 ,-1 , 0
 2327.82     .15       0 2876.36     .07       0 4938.97    .032       0
  4993.4    .015       0    5010    .032       0 5045.34     .07       0
#Block Obstruct= 3 ,-1
 2515.82 4927.18    30.2 5299.0910006.94   30.21 9476.3811298.25   35.06
Bank Sta=4983.22,5016.78
XS Rating Curve= 0
Exp/Cntr=.5,.3

Type RM Length L Ch R = 1 ,7729.513,408.65,408.99,406.65
XS GIS Cut Line= 6
     3188822.686    13810168.864     3188856.631    13808308.975
     3188821.958    13807508.479     3188819.756    13807474.998
     3188981.668    13804873.636     3189139.833    13802332.467
#Sta/Elev= 30
 2320.09   32.22 2869.41   28.97 3310.45   31.03 4953.69   29.63    4969   29.36
  4983.4    21.4 4989.75   17.71 4996.16   17.72    4999    21.7    5015   29.25
 5035.34    29.6 6140.86   28.09 6409.34   31.03 6830.97   29.23 6859.33    32.6
 6887.62    22.8 6924.53   19.98 7011.44   31.98 7057.81   28.87 7095.31   30.96
 7442.69   30.46 7499.24   27.89 7774.04   27.09 8352.17   30.87 8720.35   29.66
 8840.11   42.16 9133.76   48.83 9486.11   42.15 9662.36   30.8410167.57   29.04
#Mann= 6 ,-1 , 0
 2320.09     .15       0 2869.41     .07       0 4953.69    .032       0
  4983.4    .015       0    4999    .032       0 5035.34     .07       0
#XS Ineff= 2 , 0
       0    4969      31    5015       0      31
Permanent Ineff=
       F       F
#Block Obstruct= 4 ,-1
 2572.35 4886.69   30.31 5208.24 8531.94   25.02 5233.45 8886.35   30.29
 9246.9611514.17   35.37
Bank Sta=4969,5015
XS Rating Curve= 0
Exp/Cntr=.5,.3

Type RM Length L Ch R = 3 ,7521.9  ,,,
BEGIN DESCRIPTION:
Sam Houston Toll Road
END DESCRIPTION:
Bridge Culvert--1,0,-1,-1, 0
Deck Dist Width WeirC Skew NumUp NumDn MinLoCord MaxHiCord MaxSubmerge Is_Ogee
58,284,2.6,0, 21, 21, , , .95, 0, 0,0,,
    2300    2690    2980    4010    4100 4930.77  4939.4 4939.41 4946.82 4954.71
 5023.59  5031.8 5039.02 5039.03 5062.37    5500    5900    6350    6767    7700
   10500
    40.8    48.6    48.5    31.1    31.2   32.57   32.57   35.58   35.78    35.8
    35.8   35.86   35.62   32.68   32.68      51      51    41.4    35.6    41.4
    41.4
                                                                           28.92
    28.9
        
    2300    2690    2980    4010    4100 4930.77  4939.4 4939.41 4946.82 4954.71
 5023.59  5031.8 5039.02 5039.03 5062.37    5500    5900    6350    6767    7700
   10500
    40.8    48.6    48.5    31.1    31.2   32.57   32.57   35.58   35.78    35.8
    35.8   35.86   35.62   32.68   32.68      51      51    41.4    35.6    41.4
    41.4
                                                                           28.92
    28.9
        
BR Coef=-1 , 0 , 0 ,, 0 ,,,.8,0,,1,
WSPro=,,,, 1 ,,,, 0 ,,,, 0 ,,,,-1 ,-1 ,-1 , 0 , 0 , 0 , 0 , 0
BC Design=,, 0 ,, 0 ,,,,,,
BC HTab HWMax=48.83

Type RM Length L Ch R = 1 ,7320.519,80.32,80.4,80.03
XS GIS Cut Line= 6
 3189307.297930613809324.9163968     3189227.676    13807486.695
     3189226.861    13807474.293     3189277.494    13806660.789
     3189388.324    13804880.146     3189561.527    13802097.393
#Sta/Elev= 30
    3187   27.13 4531.49   28.87 4916.04   30.87    4951   29.63    4959   29.36
    4994   17.71 5006.16   17.72    5010    21.7 5016.78   24.36 5045.34    29.6
 5063.95   30.27 6385.42   29.01 6498.95   31.33 6555.55   20.13 6584.15   22.67
 6619.81   29.14  6762.7   31.02 7380.37   27.53 7425.78   30.28 7561.04   30.65
 7899.02   28.62 8664.21    30.8  8758.1   27.54 9154.11   28.27 9185.71   22.05
 9244.29    28.6 9364.52   26.58 9419.84   29.14 9838.86   27.8510426.68   30.09
#Mann= 4 ,-1 , 0
    3187     .07       0 4531.49     .12       0 4916.04    .032       0
 5063.95     .07       0
#XS Ineff= 3 ,-1
 3216.78 4945.88   30.77 5091.82 6489.31   30.19  6723.610687.09    30.8
Permanent Ineff=
       F       F       F
#Block Obstruct= 3 ,-1
 4302.29 4784.08      29 6459.61 6653.01   29.43 8608.9710713.64   29.78
Bank Sta=4951,5045.34
XS Rating Curve= 0
Exp/Cntr=.5,.3

Type RM Length L Ch R = 1 ,7240.12 ,725.97,733.81,734.45
XS GIS Cut Line= 6
 3189387.221083213809321.4344385     3189307.563    13807482.338
     3189307.024    13807474.152      3189357.34    13806665.759
     3189468.398    13804881.448     3189644.563    13802051.105
#Sta/Elev= 30
    3191   27.13 4537.62   29.51 4742.73   28.79 4917.55   31.56 4953.69   29.63
    4964   28.14 4989.75   17.71 5035.34    29.6 5037.49   29.57 6436.84   29.32
 6480.45   19.37 6561.53    29.6 6915.93   30.48 7381.25   27.63 7519.11   31.56
 7756.92   31.76 7771.95   29.03 7926.87   28.28 8382.31   31.47 8553.46   28.72
 8621.84   31.06 8718.78   28.07 9075.83   27.85  9126.2   22.22    9191   29.16
 9755.81   27.79 10273.3   30.4310404.83   29.7810444.49   27.2310473.56   29.08
#Mann= 4 ,-1 , 0
    3191     .07       0 4537.62     .12       0 4917.55    .032       0
 5037.49     .07       0
#XS Ineff= 3 ,-1
 3036.41 4893.06   31.16 5038.04  7656.4    29.6 7704.0410687.09    31.6
Permanent Ineff=
       F       F       F
#Block Obstruct= 5 ,-1
 4585.69 4821.86      29 6333.33 6607.29   29.59 8643.5910896.15    29.8
 8874.49 9346.83   29.1410244.2610735.49   30.41
Bank Sta=4953.69,5035.34
XS Rating Curve= 0
Exp/Cntr=.3,.1

Type RM Length L Ch R = 1 ,6506.31 ,1103.89,1105.74,1107.52
XS GIS Cut Line= 6
     3190007.749    13809001.146     3190014.088    13808723.396
     3190040.238    13807577.682     3190044.308    13807504.061
      3190052.46    13806221.519     3190076.659    13802414.735
#Sta/Elev= 30
 3540.98   26.71 4577.44    29.2 4797.18   25.81 4944.99   30.08    4959   28.57
 4998.24   15.48 5036.87   27.71 5063.63   28.17 5808.42    29.4 5868.05   18.52
 5933.25   29.09 5972.38   27.76  6017.1    19.4  6104.3   18.41 6419.02   19.75
 6460.14   27.91 6550.14   29.09 8450.93   30.98 8650.18      28 8710.19   30.41
 8764.94   29.15 8800.19   22.95 8830.19   28.42 8882.69   29.67 9696.92   29.66
 9744.63   25.95 9784.55   29.17 9940.21   26.7210000.21   16.3310127.98   17.72
#Mann= 3 ,-1 , 0
 3540.98     .15       0 4944.99    .032       0 5063.63     .07       0
#XS Ineff= 2 , 0
       0 4946.38   30.78    7000       0
Permanent Ineff=
       F       F
#Block Obstruct= 3 ,-1
 5753.04 6562.75   29.01 8608.3110273.91   29.74    8722 8873.14   29.67
Bank Sta=4959,5063.63
XS Rating Curve= 0
Exp/Cntr=.3,.1

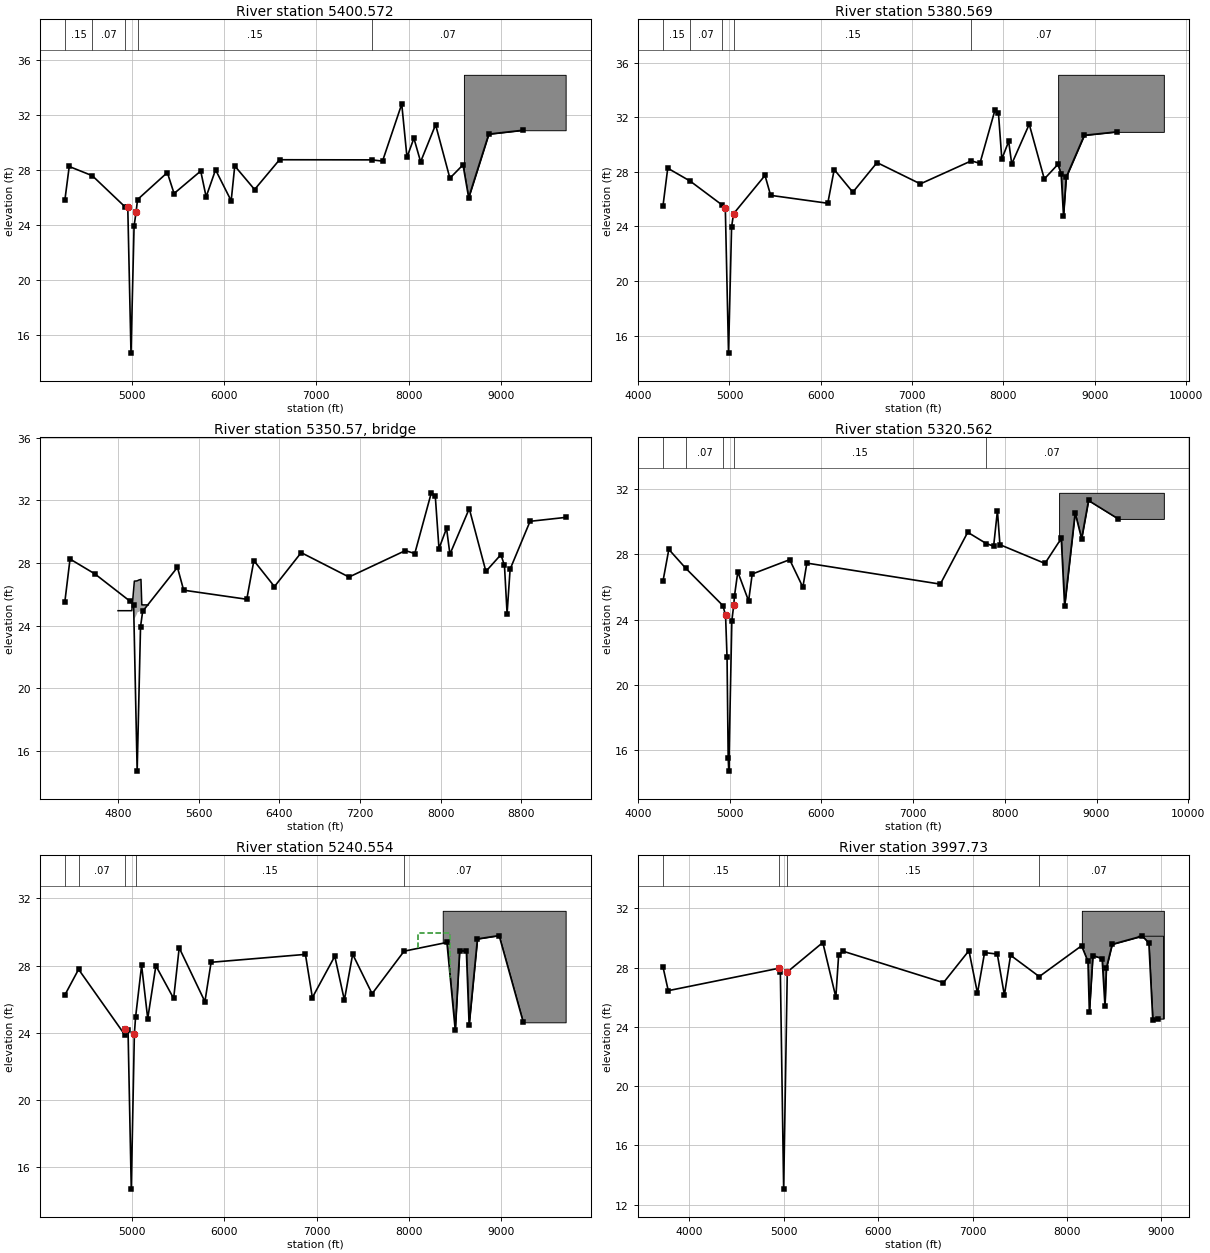
Type RM Length L Ch R = 1 ,5400.572,20,20,20
XS GIS Cut Line= 6
     3191108.374    13808304.565     3191143.465    13807649.846
     3191148.591    13807553.677     3191165.258    13807096.409
     3191274.309    13804104.624     3191302.151    13803340.794
#Sta/Elev= 30
 4272.24   25.79 4319.94   28.25  4570.3   27.58 4926.85   25.31 4954.64   25.32
 4989.69   14.71 5023.15   23.94  5044.5   24.92 5060.57   25.85 5383.68   27.81
 5456.72   26.29  5745.6   27.92 5804.53   26.05 5906.58   28.01 6076.08   25.76
 6114.83   28.29  6329.9   26.58  6600.3   28.74 7600.56   28.73 7717.19   28.64
 7925.53   32.78 7982.34   28.92 8057.39    30.3 8130.28   28.59 8292.48   31.28
 8447.65    27.4 8589.74   28.37 8650.99   25.99 8869.08    30.6 9239.89   30.88
#Mann= 5 ,-1 , 0
 4272.24     .15       0  4570.3     .07       0 4926.85    .032       0
 5060.57     .15       0 7600.56     .07       0
#Block Obstruct= 1 ,-1
 8599.74 9702.74    34.9
Bank Sta=4954.64,5044.5
XS Rating Curve= 0
Exp/Cntr=.5,.3

Type RM Length L Ch R = 1 ,5380.569,60.01,60.01,60
XS GIS Cut Line= 6
     3191128.376    13808305.076     3191163.437    13807650.914
     3191168.571    13807554.573     3191185.245    13807097.137
     3191294.275     13804105.94     3191322.115    13803342.162
#Sta/Elev= 30
 4272.37   25.52 4323.96   28.26 4570.38   27.31 4918.05   25.57 4954.64   25.32
 4989.69   14.71 5023.15   23.94  5044.5   24.92 5389.14   27.73 5450.77   26.27
 6076.72   25.69 6147.25   28.16 6351.32    26.5 6616.39   28.67 7090.81   27.11
 7649.79    28.8 7742.96   28.61 7906.85   32.49 7946.09    32.3 7982.99   28.93
 8058.04   30.22 8091.65   28.57 8283.29   31.48 8448.29   27.47 8597.14   28.54
 8632.41   27.85 8658.43   24.78 8688.45   27.61 8886.29   30.67 9239.16   30.92
#Mann= 5 ,-1 , 0
 4272.37     .15       0 4570.38     .07       0 4918.05    .032       0
  5044.5     .15       0 7649.79     .07       0
#Block Obstruct= 1 ,-1
 8599.74  9757.5    35.1
Bank Sta=4954.64,5044.5
XS Rating Curve= 0
Exp/Cntr=.5,.3

Type RM Length L Ch R = 3 ,5350.57 ,,,
BEGIN DESCRIPTION:
Wooden Footbridge at Country Road
END DESCRIPTION:
Bridge Culvert--1,0,-1,-1, 0
Deck Dist Width WeirC Skew NumUp NumDn MinLoCord MaxHiCord MaxSubmerge Is_Ogee
23,4,2.6,0, 10, 10, , , .95, 0, 0,0,,
    4800 4936.52 4961.75  4983.7 4993.67 5005.92 5027.56 5035.94 5035.95    5100
   24.96   24.96   26.85   26.86   26.88   26.92   26.96   25.33   25.33   25.33
    24.2    24.2   24.42   24.69   24.86   24.88   24.98   25.05
    4800 4936.52 4961.75  4983.7 4993.67 5005.92 5027.56 5035.94 5035.95    5100
   24.96   24.96   26.85   26.86   26.88   26.92   26.96   25.33   25.33   25.33
    24.2    24.2   24.42   24.69   24.86   24.88   24.98   25.05
Pier Skew, UpSta & Num, DnSta & Num=  ,4987, 2 ,4987, 2 , 0 , 0 , 0 ,,
     1.2     1.2
       0
     1.2     1.2
       0
Pier Skew, UpSta & Num, DnSta & Num=  ,5009, 2 ,5009, 2 , 0 , 0 , 0 ,,
     1.2     1.2
       0
     1.2     1.2
       0
BR Coef=-1 , 1 , 1 ,1.25, 0 ,,,.8,0,2,0,
WSPro=,,,, 1 ,,,, 0 ,,,, 0 ,,,,-1 ,-1 ,-1 , 0 , 0 , 0 , 0 , 0
BC Design=,, 0 ,, 0 ,,,,,,
BC HTab HWMax=32.49

Type RM Length L Ch R = 1 ,5320.562,80.01,80.01,80
XS GIS Cut Line= 6
      3191188.38    13808306.608     3191223.351    13807654.116
     3191228.513    13807557.263     3191245.205    13807099.323
      3191354.17    13804109.889     3191382.004    13803346.264
#Sta/Elev= 30
 4272.74   26.38 4335.98   28.31 4520.95   27.15 4926.17   24.86 4954.64   24.26
 4970.83   21.68 4983.24   15.53 4989.69   14.71 5023.15   23.94  5044.5   24.92
 5051.77   25.45 5087.97   26.93 5206.04   25.15 5245.25    26.8 5653.84   27.68
 5797.83   25.99 5840.95   27.47 7296.19   26.18 7595.37   29.36 7797.33   28.67
 7877.91   28.51 7919.34   30.68 7946.53    28.6 8437.59   27.45  8615.3   28.98
 8651.93   24.84 8766.59   30.55  8837.1   28.97 8912.58   31.31 9236.95   30.18
#Mann= 5 ,-1 , 0
 4272.74     .15       0 4520.95     .07       0 4926.17    .032       0
 5051.77     .15       0 7797.33     .07       0
#Block Obstruct= 2 ,-1
 8591.92 9734.03   31.78   1000010289.44   23.93
Bank Sta=4954.64,5044.5
XS Rating Curve= 0
Exp/Cntr=.5,.3

Type RM Length L Ch R = 1 ,5240.554,1400,1242.82,1077.52
XS GIS Cut Line= 6
     3191268.385    13808308.652     3191303.237    13807658.385
     3191308.436    13807560.849     3191325.152    13807102.237
     3191434.032    13804115.155     3191461.859    13803351.733
#Sta/Elev= 30
 4275.73   26.25 4424.55   27.78 4927.07   23.87 4931.85   24.26 4959.64   24.16
 4994.69   14.71 5028.15   23.94    5041   24.92 5106.49   28.01 5172.72   24.85
 5260.93   27.99 5453.24   26.05 5513.28   29.06 5791.48   25.86 5858.51    28.2
 6879.18   28.67 6954.23    26.1 7196.86   28.56 7300.62   25.95 7390.32   28.68
 7600.73   26.33 7946.71   28.86  8410.2   29.38 8500.26   24.17 8547.86   28.88
 8620.34   28.89 8650.36   24.49 8740.42   29.59 8975.14   29.79 9236.52   24.63
#Mann= 5 ,-1 , 0
 4275.73     .15       0 4424.55     .07       0 4927.07    .032       0
    5041     .15       0 7946.71     .07       0
#XS Ineff= 1 ,-1
 8094.06  8447.1   29.97
Permanent Ineff=
       F
#Block Obstruct= 1 ,-1
 8365.06 9694.92   31.26
Bank Sta=4931.85,5028.15
XS Rating Curve= 0
Exp/Cntr=.3,.1

Type RM Length L Ch R = 1 ,3997.73 ,1078.82,1249.58,1389.33
XS GIS Cut Line= 6
     3193060.852    13807625.947     3192469.918    13807065.711
     3192042.034    13807031.617     3191968.902    13807024.918
     3191581.949    13806891.641     3191544.725    13803375.013
#Sta/Elev= 30
  3720.7   28.03 3776.02   26.44 4953.95   27.96 4963.28   27.69 4998.36   13.04
 5036.72    27.7 5412.93   29.69 5551.08      26 5581.08   28.88  5629.3    29.1
 6691.14   26.98 6960.89   29.14 7051.16   26.27  7126.5   29.01 7261.17   28.91
 7336.18   26.13  7401.8   28.83 7705.42   27.39 8153.66   29.47 8221.23   28.41
 8236.23   24.99 8273.32   28.81 8371.24   28.61 8401.24   25.43 8416.24   27.96
 8477.77   29.57 8797.12   30.13 8866.26   29.66 8908.22   24.43 8963.76   24.56
#Mann= 4 ,-1 , 0
  3720.7     .15       0 4953.95    .032       0 5036.72     .15       0
 7705.42     .07       0
#Block Obstruct= 3 ,-1
 7529.33 8421.12   19.97 8156.76 9025.08   31.83 8748.99 9016.19   30.15
Bank Sta=4953.95,5036.72
XS Rating Curve= 0
Exp/Cntr=.3,.1

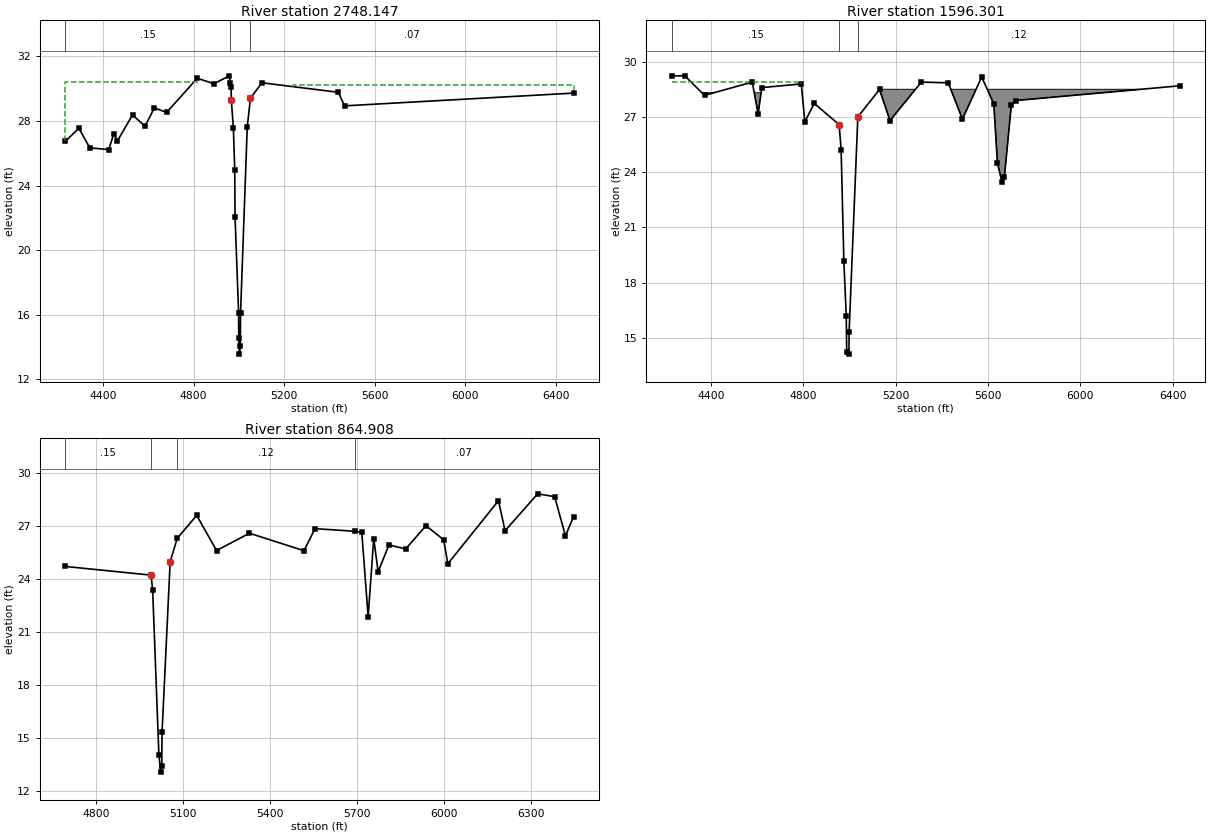
Type RM Length L Ch R = 1 ,2748.147,1146.7,1151.85,1154.9
XS GIS Cut Line= 5
     3193037.828      13807579.9     3193026.912    13806850.754
     3193029.006     13806776.14     3193053.177    13806121.751
 3193082.183585913805336.4466781
#Sta/Elev= 30
 4233.45   26.74    4294   27.55 4342.16   26.34 4425.67   26.23 4447.99   27.21
    4464   26.77 4530.88   28.38 4585.99   27.67 4627.02   28.82  4680.9   28.53
 4816.71   30.65 4890.18   30.31 4958.17    30.8  4962.8   30.36 4965.93   30.08
    4967   29.28    4976   27.59    4982   24.99 4983.38   22.07 4999.21   16.08
 4999.79   14.54 5002.77   13.56 5006.52   14.09 5007.73   16.11 5037.32   27.66
 5051.51   29.42 5102.07   30.37 5439.41   29.78 5467.18   28.94    6478   29.73
#Mann= 3 ,-1 , 0
 4233.45     .15       0  4962.8    .032       0 5051.51     .07       0
#XS Ineff= 2 ,-1
 4097.78 4818.12   30.42 5238.59    6500   30.26
Permanent Ineff=
       F       F
#Block Obstruct= 2 , 0
         4884.53    30.2
Bank Sta=4967,5051.51
XS Rating Curve= 0
Exp/Cntr=.3,.1

Type RM Length L Ch R = 1 ,1596.301,737.18,731.39,731.62
XS GIS Cut Line= 5
     3194146.487    13807641.602     3194169.052    13806908.692
     3194176.869    13806836.739     3194204.347    13806152.449
 3194232.848486413805442.6709174
#Sta/Elev= 30
 4230.17   29.23 4287.17   29.23 4372.31   28.17 4579.16   28.89 4604.45   27.17
 4620.46   28.59 4791.29   28.79 4806.73   26.74 4847.58   27.73 4955.11   26.58
 4963.81   25.23  4975.7   19.15 4985.96   16.21 4988.09   14.24 4997.51   14.12
 4998.35   15.32 5036.19      27 5130.12   28.49 5175.21    26.8 5311.19   28.89
 5427.68   28.85 5489.01   26.88 5572.52   29.17 5624.92    27.7 5640.53   24.49
 5659.96   23.49 5670.55   23.72 5700.58   27.63 5720.65   27.89    6431   28.69
#Mann= 3 ,-1 , 0
 4230.17     .15       0 4955.11    .032       0 5036.19     .12       0
#XS Ineff= 1 ,-1
 4231.42 4788.79   28.87
Permanent Ineff=
       F
#Block Obstruct= 2 ,-1
 4230.17 4668.56   28.31 5129.12 6397.61    28.5
Bank Sta=4955.11,5036.19
XS Rating Curve= 0
Exp/Cntr=.3,.1

Type RM Length L Ch R = 1 ,864.908 ,846.16,864.91,862.68
XS GIS Cut Line= 5
     3194887.464     13807249.34     3194899.112    13806944.269
     3194906.462    13806884.391     3194933.422    13806282.915
     3194968.528    13805499.701
#Sta/Elev= 30
 4693.45   24.69 4989.28    24.2 4994.84   23.34 5016.29   14.03 5022.45   13.05
 5026.07   13.39 5027.24   15.33 5055.16   24.96 5079.42   26.28 5146.58   27.58
 5215.02   25.59 5328.46   26.57 5516.42   25.58 5554.19   26.83 5691.92   26.68
  5715.5   26.62 5737.31   21.85 5756.66   26.27 5771.68   24.39 5809.16   25.91
 5866.65   25.68 5936.84      27  5997.9   26.19 6011.92   24.84 6186.54   28.41
 6209.09   26.71 6321.52    28.8 6380.04   28.64 6417.32   26.42 6445.15    27.5
#Mann= 4 ,-1 , 0
 4693.45     .15       0 4989.28    .032       0 5079.42     .12       0
 5691.92     .07       0
#Block Obstruct= 2 , 0
                         5146.19           27.43
Bank Sta=4989.28,5055.16
XS Rating Curve= 0
Exp/Cntr=.3,.1

Chan Stop Cuts=-1